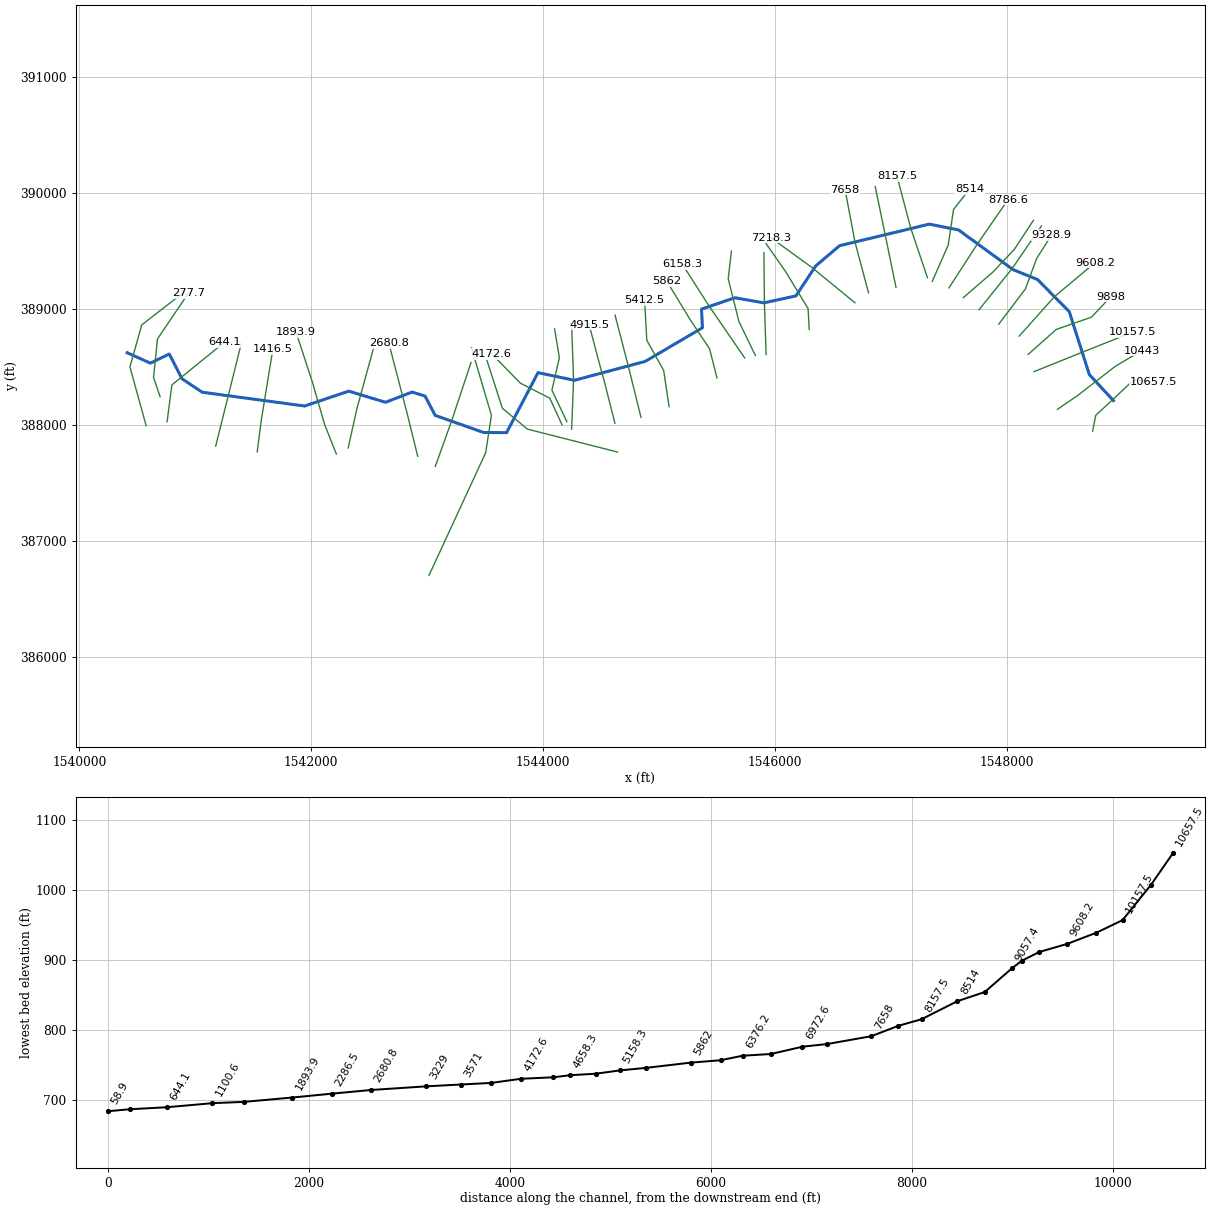
--- GRASSYBR.prj (project) ---

Proj Title=GRASSYBR
Current Plan=p01
Default Exp/Contr=0,0
English Units
Geom File=g01
Flow File=f01
Plan File=p01
BEGIN DESCRIPTION:
END DESCRIPTION:
DSS Export Rating Curves= 0
DSS Export Rating Curve Sorted= 0
DSS Export Volume Flow Curves= 0
DXF OffsetX= 0
DXF OffsetY= 0
DXF ScaleX= 0
DXF ScaleY= 0

--- GRASSYBR.p01 (plan) ---

Plan Title=Floodplain
Program Version=4.00
Geom File=g01
Flow File=f01
K Sum by GR=0
Std Step Tol=0.01
Critical Tol=0.01
Num of Std Step Trials=20
Max Error Tol=0.3
Flow Tol Ratio=0.001
Split Flow NTrial=30
Split Flow Tol=0.02
Split Flow Ratio=0.02
Log Output Level=0
Friction Slope Method=1
Unsteady Friction Slope Method=2
Unsteady Bridges Friction Slope Method=1
Global Log Level=0
CheckData=False
Run HTab=0
Run UNet=0
Run PostProcess=0
UNET Theta=0
UNET Theta Warmup=0
UNET ZTol=0
UNET ZSATol=0
UNET MxIter=0
UNET MaxInSteps=0
UNET DtIC=0
UNET DtMin=0
UNET MaxCRTS=0
UNET WFStab=0
UNET SFStab=0
UNET WFX=0
UNET SFX=0
UNET DSS MLevel=0
UNET DZMax Abort=0
UNET Convert EG Bridges=0
UNET Use Existing IB Tables=0
UNET Froude Limit=0
UNET Froude Power=0
Write IC File=0
Echo Input=False
Echo Output=False
Write Detailed=0

--- GRASSYBR.f01 (steady flow) ---

Flow Title=NFF Regression Equation
Program Version=4.00
Number of Profiles=1
Profile Names=P100yr
River Rch & RM=GRASSYBR,Main      ,10657.5
     344
River Rch & RM=GRASSYBR,Main      ,3873.1
     347
River Rch & RM=GRASSYBR,Main      ,3571
     484
River Rch & RM=GRASSYBR,Main      ,2680.8
     496
River Rch & RM=GRASSYBR,Main      ,277.7
     550
Boundary for River Rch & Prof#=GRASSYBR,Main      ,1
Up Type=0
Dn Type=3
Dn Slope=0.011171

--- GRASSYBR.g01 (geometry) ---

Geom Title=USGS 10m DEM
Program Version=4.00

River Reach=GRASSYBR        ,Main
Reach XY= 30
      1548920.85      388207.026     1548713.083      388430.749
     1548540.023      388973.285     1548265.625      389250.504
     1548055.867      389334.823     1547584.989      389677.419
     1547332.562      389727.801     1546558.225      389541.925
     1546352.588       389367.58     1546181.483      389109.172
     1545905.197       389049.26     1545654.978      389093.029
     1545367.234      388995.514     1545375.156      388834.518
     1544881.127      388544.428     1544270.167      388381.604
     1543956.532      388447.705     1543685.355      387930.217
     1543486.064      387932.047     1543069.596      388079.346
     1542981.835      388245.767     1542870.293      388280.026
     1542640.753      388192.111      1542323.69      388288.262
     1541943.039      388160.032     1541058.993      388278.944
     1540884.474       388395.54     1540775.655      388608.522
     1540612.434      388529.452     1540411.619      388619.549

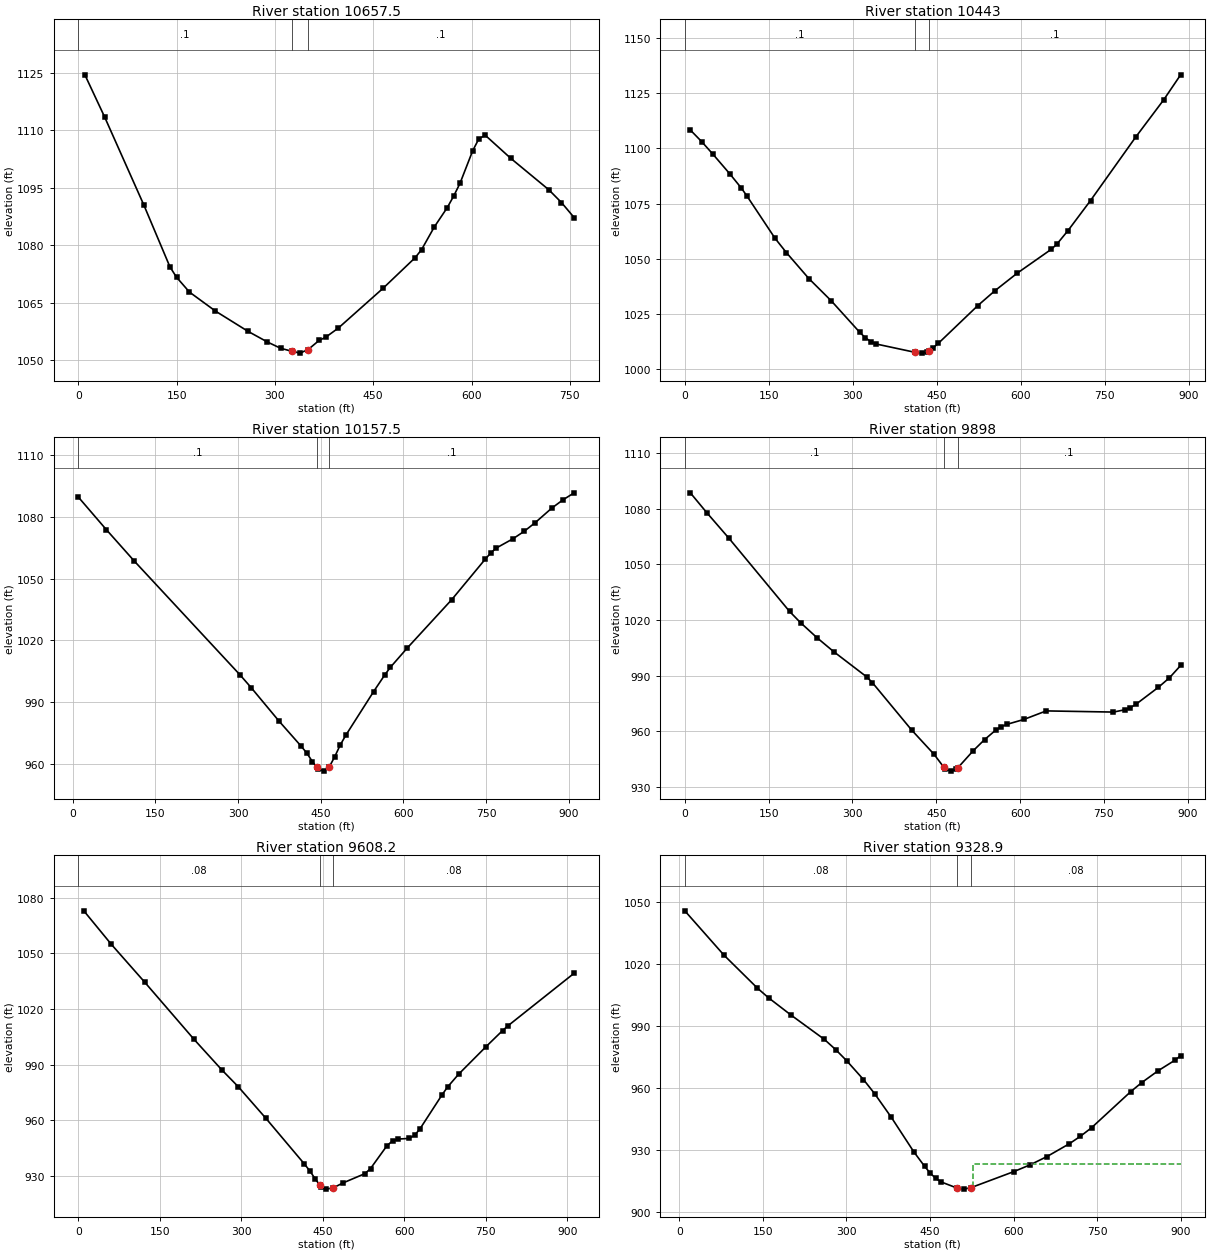
Type RM Length L Ch R = 1 ,10657.5 ,216.9,214.5,211.9
XS GIS Cut Line= 5
     1548741.461      387942.778     1548768.415      388079.998
     1548914.224      388214.515     1549092.083      388381.831
     1549265.745      388368.759
#Sta/Elev= 30
      10 1124.52      40 1113.56    99.9 1090.56   139.8 1074.38   149.8 1071.69
   169.6  1067.8   209.3 1062.84   258.9 1057.56   288.6 1054.77   308.5 1053.15
   325.7 1052.36   338.2 1051.87   350.7 1052.81   367.5  1055.2   377.3    1056
   396.8 1058.42   465.2 1068.83     514 1076.79   523.8  1078.9   543.3 1084.84
   562.9 1089.84   572.6 1092.82   582.4  1096.2   601.8 1104.72   611.4 1107.89
   621.1 1108.72   659.8 1102.73   717.9 1094.52   737.2 1091.19   756.6 1087.25
#Mann= 3 , 0 , 0
       0      .1       0   325.7    .045       0   350.7      .1       0
Bank Sta=325.7,350.7
XS Rating Curve= 0 ,0
Exp/Cntr=0.3,0.1

Type RM Length L Ch R = 1 ,10443   ,293.6,285.5,277.2
XS GIS Cut Line= 4
     1548437.447      388131.053     1548612.065      388250.529
     1548938.326      388503.266     1549163.491      388636.527
#Sta/Elev= 30
    10.1 1108.16    30.2 1102.95    50.4 1097.24    80.6 1088.35   100.8 1082.05
   110.8 1078.48   161.2 1059.29   181.4 1052.85   221.6  1041.1   261.9 1030.97
   312.2  1016.9   322.3 1014.41   332.4 1012.58   342.4 1011.49   410.5  1007.8
     423 1007.39     433 1007.95   435.5 1008.37   443.1 1009.65   453.2 1011.86
   523.6 1028.89   553.8 1035.53   594.1 1043.55   654.5 1054.26   664.5 1056.55
   684.7 1062.77   724.9 1076.34   805.4 1104.94   855.7 1121.87   885.9 1133.15
#Mann= 3 , 0 , 0
       0      .1       0   410.5    .045       0   435.5      .1       0
Bank Sta=410.5,435.5
XS Rating Curve= 0 ,0
Exp/Cntr=0.3,0.1

Type RM Length L Ch R = 1 ,10157.5 ,260.8,259.5,258.3
XS GIS Cut Line= 3
     1548236.774      388456.678      1548659.09       388626.27
     1549081.851      388794.327
#Sta/Elev= 30
    10.1 1089.55    60.7  1073.8   111.2 1058.62   303.4 1003.28   323.6   997.1
   374.2  980.84   414.6  968.59   424.8  965.27   434.9  961.15   442.6  958.53
     445  957.71   455.1  956.51   465.2  958.39   475.3  963.42   485.4  969.17
   495.5  973.91   546.1  995.16   566.3 1003.23   576.4  1006.9   606.7 1016.16
   687.6  1039.7   748.3  1059.3   758.4 1062.37   768.5 1064.79   798.8 1069.28
     819 1072.87   839.3 1077.13   869.6 1084.24   889.8 1088.22     910 1091.61
#Mann= 3 , 0 , 0
    10.1      .1       0   442.6    .045       0   465.2      .1       0
Bank Sta=442.6,465.2
XS Rating Curve= 0 ,0
Exp/Cntr=0.3,0.1

Type RM Length L Ch R = 1 ,9898    ,275.7,289.8,299.9
XS GIS Cut Line= 4
      1548184.71       388604.36     1548428.257      388820.335
     1548731.541      388926.026     1548896.969      389100.644
#Sta/Elev= 30
     9.9  1088.6    39.5 1077.85    78.9 1064.14   187.4 1024.69   207.1 1018.62
   236.7 1010.47   266.3 1003.03   325.5  989.39   335.6  986.31   405.8  960.79
     446  947.67   463.6  940.65     466  939.77   476.1   938.6   486.1  939.64
   488.6  940.41   516.2  949.63   536.3  955.56   556.4  960.72   566.4  962.55
   576.4  963.82   606.5  966.43   646.7  971.06     767  970.43     787  971.65
     797  972.77     807  974.57   847.1  983.71   867.2   988.9   887.2  995.54
#Mann= 3 , 0 , 0
       0      .1       0   463.6    .045       0   488.6      .1       0
Bank Sta=463.6,488.6
XS Rating Curve= 0 ,0
Exp/Cntr=0.3,0.1

Type RM Length L Ch R = 1 ,9608.2  ,268.9,279.3,293.7
XS GIS Cut Line= 3
     1548108.387       388762.65     1548412.662      389103.238
     1548762.559      389395.549
#Sta/Elev= 30
    10.1 1073.06    60.9 1054.89   121.8 1034.62   213.1 1003.55   263.9  987.16
   294.3  978.02   345.1  960.96   416.1  936.23   426.3  932.41   436.4     928
   444.2  924.97   446.6  924.04   456.7  922.65   469.2  923.36   487.1  925.99
   527.6  931.04   537.8  933.78   568.2  946.17   578.3  948.73   588.4   949.7
   608.7  950.06   618.8  951.69     629  955.31   669.5  973.64   679.6  977.85
   699.9  984.75   750.5  999.68   780.9 1008.36   791.1    1011   912.6 1039.34
#Mann= 3 , 0 , 0
       0     .08       0   444.2    .045       0   469.2     .08       0
Bank Sta=444.2,469.2
XS Rating Curve= 0 ,0
Exp/Cntr=0.3,0.1

Type RM Length L Ch R = 1 ,9328.9  ,180.4,171.4,164.4
XS GIS Cut Line= 4
     1547931.973      388866.288     1548161.734      389169.572
     1548258.234      389431.499       1548386.9      389633.689
#Sta/Elev= 30
      10 1045.95    80.1 1024.51   140.2 1008.48   160.2 1003.78   200.3  995.45
   260.3  983.62   280.4  978.71   300.4  973.25   330.4  964.16   350.4  957.32
   380.5  945.79   420.4  929.24   440.3  921.99   450.3  918.75   460.2  916.17
   470.2  914.45   497.6   911.6   510.1  911.01   522.6  911.66   599.8  919.47
   629.7  922.83   659.6   926.8   699.6     933   719.5  936.62   739.5  940.77
   809.4  958.18   829.4  962.64   859.3  968.47   889.3  973.55   899.3  975.71
#Mann= 3 , 0 , 0
      10     .08       0   497.6    .045       0   522.6     .08       0
#XS Ineff= 2 , 0
                          526.98          922.97
Permanent Ineff=
       F       F
Bank Sta=497.6,522.6
XS Rating Curve= 0 ,0
Exp/Cntr=0.3,0.1

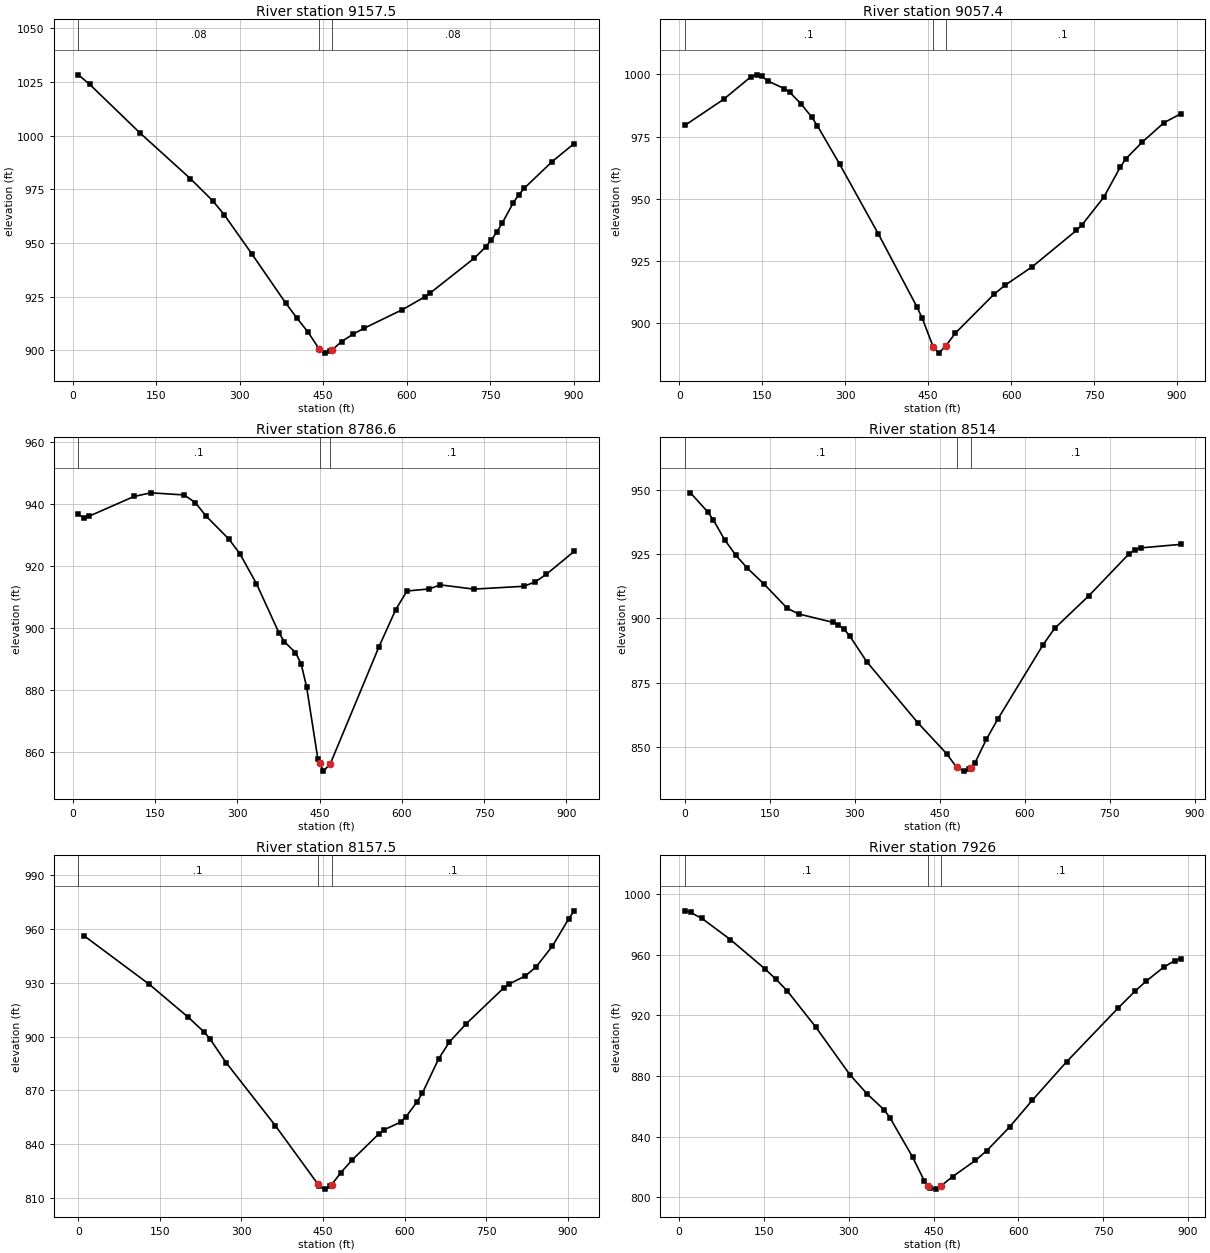
Type RM Length L Ch R = 1 ,9157.5  ,102.2,100.1,95.9
XS GIS Cut Line= 3
      1547761.47      388990.098      1548045.56      389343.118
     1548299.591      389711.807
#Sta/Elev= 30
    10.1 1028.37    30.2    1024   120.8 1001.29   211.5  979.97   251.7  969.62
   271.9  963.27   322.2  944.77   382.6  922.02   402.8     915   422.9  908.41
   443.1  900.48   453.1  898.66   463.1   899.5   465.6  900.07     483  904.01
   502.9   907.4   522.8  910.16   592.4  918.94   632.2  924.82   642.2  926.66
   721.8  942.99   741.7   948.1   751.6  951.22   761.6  954.94   771.5   959.2
   791.4   968.7   801.4  972.45   811.3  975.54   861.1  987.87   900.9  996.35
#Mann= 3 , 0 , 0
    10.1     .08       0   443.1    .045       0   465.6     .08       0
Bank Sta=443.1,465.6
XS Rating Curve= 0 ,0
Exp/Cntr=0.3,0.1

Type RM Length L Ch R = 1 ,9057.4  ,265.9,270.9,275
XS GIS Cut Line= 4
     1547625.489      389093.826     1547882.647      389316.043
     1548067.129      389511.707     1548230.648      389760.479
#Sta/Elev= 30
      10  979.47      80  989.95   129.9  999.12   139.9  999.84   149.9  999.17
   159.9  997.39   189.9   994.3   199.9  992.77   219.9  988.23   239.9  982.71
   249.9  979.26   289.9  963.92   359.8  935.87   429.5  906.54   439.5  901.77
   459.4  890.18   469.3  887.82   481.8  890.71   499.2  895.87   568.9  911.47
   588.9  915.13   638.6  922.65   717.9  937.18   727.9  939.36   767.6  950.58
   797.3  962.67   807.3  966.01     837  972.74   876.7  980.62   906.5  984.12
#Mann= 3 , 0 , 0
      10      .1       0   459.4    .045       0   481.8      .1       0
Bank Sta=459.4,481.8
XS Rating Curve= 0 ,0
Exp/Cntr=0.3,0.1

Type RM Length L Ch R = 1 ,8786.6  ,260.8,272.6,285.3
XS GIS Cut Line= 3
     1547501.587      389177.931     1547750.207      389561.402
     1548010.898       389937.19
#Sta/Elev= 30
    10.2  936.64    20.3  935.57    30.5  936.09   111.7  942.39   142.2  943.57
   203.1  942.89   223.4  940.42   243.7  935.98   284.4   928.7   304.7  923.95
   335.1  914.24   375.8   898.5   385.9  895.56   406.2  892.03   416.4   888.5
   426.5  880.95   446.9  857.86  450.84  856.37     457   853.8   469.5  856.07
   558.6  893.98   589.1  905.92   609.5   911.9   650.1  912.57   670.4  913.88
   731.4  912.51   822.9  913.43   843.2  914.84   863.6  917.28   914.4  924.68
#Mann= 3 , 0 , 0
    10.2      .1       0  450.84    .045       0   469.5      .1       0
Bank Sta=450.84,469.5
XS Rating Curve= 0 ,0
Exp/Cntr=0.3,0.1

Type RM Length L Ch R = 1 ,8514    ,343.4,356.5,367.6
XS GIS Cut Line= 4
     1547357.571      389233.905     1547495.428       389546.38
      1547541.38      389854.259     1547679.236      390028.877
#Sta/Elev= 30
      10  948.76    40.2  941.42    50.2   938.3    70.3  930.54    90.4  924.44
   110.5  919.48   140.6  913.17   180.8  903.93   200.9  901.73   261.2  898.48
   271.2  897.49   281.3  895.75   291.3  893.12   321.4  883.12   411.8  859.36
     462  847.52   479.7   842.2   492.2  840.69   502.2   841.4   504.7  842.02
   512.2  843.87   532.3  853.02   552.4  860.84   632.7  889.84   652.8  896.11
   713.5  908.83   784.3   925.1   794.4  926.58   804.5  927.37   875.3  928.74
#Mann= 3 , 0 , 0
       0      .1       0   479.7    .045       0   504.7      .1       0
Bank Sta=479.7,504.7
XS Rating Curve= 0 ,0
Exp/Cntr=0.3,0.1

Type RM Length L Ch R = 1 ,8157.5  ,234.9,231.5,230.1
XS GIS Cut Line= 3
     1547316.214      389266.072     1547171.485      389695.557
     1547054.287      390139.162
#Sta/Elev= 30
    10.1  956.38   130.9  929.09   201.4  911.02   231.6  902.53   241.7  898.95
   271.9  885.47   362.6  850.27   440.7   817.7   443.1  816.69   453.2  814.93
   463.2  816.42   465.7  817.37   483.1   824.2   503.1  831.04     553  845.84
   562.9  848.12   592.9  852.31   602.8  855.35   622.8  863.52   632.8  868.46
   662.7  887.63   682.6  897.03   712.6  906.93   782.4  927.17   792.3  929.36
   822.3  933.87   842.2  938.99   872.1  950.56   902.1  965.79     912  970.19
#Mann= 3 , 0 , 0
       0      .1       0   440.7    .045       0   465.7      .1       0
Bank Sta=440.7,465.7
XS Rating Curve= 0 ,0
Exp/Cntr=0.3,0.1

Type RM Length L Ch R = 1 ,7926    ,266.4,268,267.5
XS GIS Cut Line= 2
     1547045.097      389183.358     1546865.883      390051.853
#Sta/Elev= 30
    10.1  988.96    20.2  987.87    40.3  983.99    90.7  970.01   151.2  950.88
   171.3  943.89   191.5  936.05   241.9  912.23   302.3  880.78   332.5  868.25
   362.8  857.67   372.9  852.51   413.2  826.43   433.3  811.12     441  807.35
   443.4  806.18   453.5  805.48   463.6  807.77   483.7  813.76     524   824.4
   544.2  830.88   584.5   846.5   624.8   864.2   685.2  889.44   775.9  924.73
   806.2     936   826.3  942.72   856.6  951.71   876.7  956.18   886.8  957.41
#Mann= 3 , 0 , 0
    10.1      .1       0     441    .045       0   463.6      .1       0
Bank Sta=441,463.6
XS Rating Curve= 0 ,0
Exp/Cntr=0.3,0.1

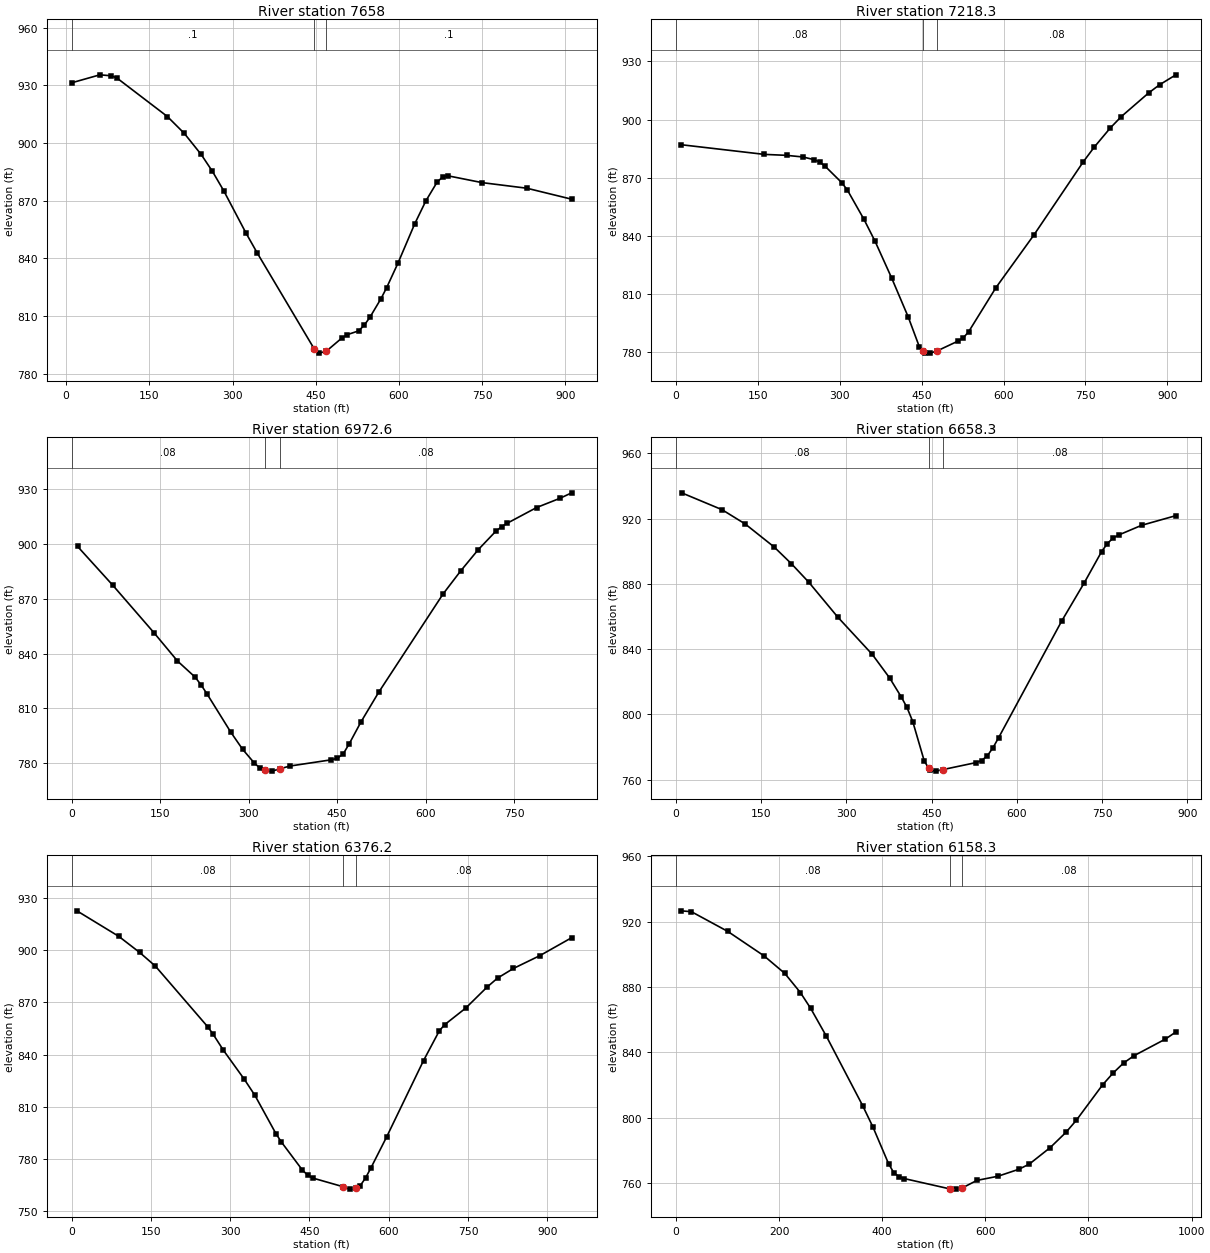
Type RM Length L Ch R = 1 ,7658    ,422.5,439.7,459
XS GIS Cut Line= 3
     1546808.182      389135.179     1546690.589      389576.284
       1546606.2      390023.119
#Sta/Elev= 30
    10.1  931.34    60.9  935.49    81.2     935    91.3  933.91   182.6  913.79
     213  905.04   243.5  894.05   263.8  885.25   284.1   875.2   324.6  852.99
   344.9  842.61  447.26  792.87   456.5  790.69     469  791.69   496.9  798.52
     507  800.32   527.2  802.26   537.4  805.22   547.5  809.29   567.7   819.1
   577.8  824.78     598  837.42   628.3  857.94   648.5  869.95   668.7  879.66
   678.8  882.42   688.9  882.91   749.6  879.41   830.4  876.49   911.2  870.78
#Mann= 3 , 0 , 0
    10.1      .1       0  447.26    .045       0     469      .1       0
Bank Sta=447.26,469
XS Rating Curve= 0 ,0
Exp/Cntr=0.3,0.1

Type RM Length L Ch R = 1 ,7218.3  ,255.2,245.7,235.5
XS GIS Cut Line= 3
     1546690.798      389050.166     1546314.457      389357.976
     1545966.762      389609.831
#Sta/Elev= 30
    10.1  886.99   162.1  882.01   202.6  881.52     233  880.67   253.2  879.28
   263.4  878.08   273.5  875.85   303.9  867.38     314  863.64   344.4  848.51
   364.6  837.26     395  818.32   425.4  798.17   445.7  782.85   453.4  780.47
   455.8  779.72   465.9  779.48   478.4  780.63   516.1  785.62   526.1   787.3
   536.1  790.53     586  813.25   655.9  840.57   745.8  878.11   765.8  885.68
   795.7  895.73   815.7  901.54   865.6  913.71   885.6  917.92   915.5  923.06
#Mann= 3 , 0 , 0
       0     .08       0   453.4    .045       0   478.4     .08       0
Bank Sta=453.4,478.4
XS Rating Curve= 0 ,0
Exp/Cntr=0.3,0.1

Type RM Length L Ch R = 1 ,6972.6  ,328.6,314.3,300.1
XS GIS Cut Line= 4
     1546296.076      388820.335     1546286.886      388999.549
     1546093.887      389316.619     1545923.864      389560.165
#Sta/Elev= 30
      10  898.71    69.8  877.42   139.6  851.43   179.4  835.97   209.5  827.08
   219.6  822.78   229.6  817.89   269.7  797.04   289.8  787.62   309.9  780.01
   319.9  777.16   327.5  776.05     340  775.67   352.5   776.9   370.1  778.46
   440.3  781.88   450.3  782.69   460.3  785.07   470.4  790.55   490.4  802.57
   520.5  818.84   629.8  872.75   659.5  885.29   689.2  896.91     719  907.01
   728.9  909.53   738.8  911.49   788.3  920.02   827.9  925.08   847.7  928.07
#Mann= 3 , 0 , 0
       0     .08       0   327.5    .045       0   352.5     .08       0
Bank Sta=327.5,352.5
XS Rating Curve= 0 ,0
Exp/Cntr=0.3,0.1

Type RM Length L Ch R = 1 ,6658.3  ,276.2,282.1,288.6
XS GIS Cut Line= 3
     1545924.533      388602.666     1545909.901      389049.625
     1545905.483      389482.047
#Sta/Elev= 30
    10.2  935.73    81.3  925.39     122  916.64   172.8  902.58   203.3  892.29
   233.8  880.99   284.6  859.69   345.6  836.71   376.1   822.3   396.4  810.76
   406.5  804.31   416.7  795.64     437  771.43   444.8  767.03   447.2  765.67
   457.3  765.24   469.8  766.18   527.7  770.44   537.7  771.71   547.8  774.57
   557.8  779.52   567.9  785.79   678.5  857.03   718.7  880.77   748.9  899.68
     759  904.62     769  907.99   779.1  909.91   819.3  915.83   879.6  921.75
#Mann= 3 , 0 , 0
       0     .08       0   444.8    .045       0   469.8     .08       0
Bank Sta=444.8,469.8
XS Rating Curve= 0 ,0
Exp/Cntr=0.3,0.1

Type RM Length L Ch R = 1 ,6376.2  ,207.8,217.9,226.9
XS GIS Cut Line= 4
      1545831.96       388595.17     1545689.508      388889.264
     1545597.604      389256.881     1545625.175      389495.832
#Sta/Elev= 30
     9.9  922.67    89.1  908.01   128.7  898.74   158.4  890.91   257.5  856.03
   267.4  851.89   287.2  842.54   326.8  825.83   346.7  816.67   386.6  794.61
   396.6  789.94   436.5  773.76   446.4  770.83   456.4  769.11   513.7  764.14
   526.2  762.76   538.7   763.3   546.2  764.81   556.1  769.17   566.1  774.83
     596  792.73   665.8  836.59   695.7  853.71   705.7  857.21   745.8  866.81
   785.9  878.79   805.9  884.02     836  889.56   886.1  896.94   946.2  907.23
#Mann= 3 , 0 , 0
       0     .08       0   513.7    .045       0   538.7     .08       0
Bank Sta=513.7,538.7
XS Rating Curve= 0 ,0
Exp/Cntr=0.3,0.1

Type RM Length L Ch R = 1 ,6158.3  ,296.4,296.3,297.4
XS GIS Cut Line= 3
     1545739.864      388574.356     1545432.224      389021.903
     1545202.415      389380.952
#Sta/Elev= 30
    10.1  926.58    30.2  926.04   100.6     914     171  899.02   211.2   888.3
   241.4   876.6   261.5  866.85   291.7  849.93   362.1  807.45   382.2  794.26
   412.3  771.96   422.4  766.42   432.5  763.97   442.5  762.82   530.6  756.52
   543.1  756.34   555.6  757.13   583.7  761.68   624.3  764.21   664.9  768.48
   685.2  771.64   725.8  781.76   756.2  791.03   776.5  798.49   827.3  820.12
   847.6  827.31   867.9  833.46   888.2  837.94   949.1  848.12   969.4  852.46
#Mann= 3 , 0 , 0
       0     .08       0   530.6    .045       0   555.6     .08       0
Bank Sta=530.6,555.6
XS Rating Curve= 0 ,0
Exp/Cntr=0.3,0.1

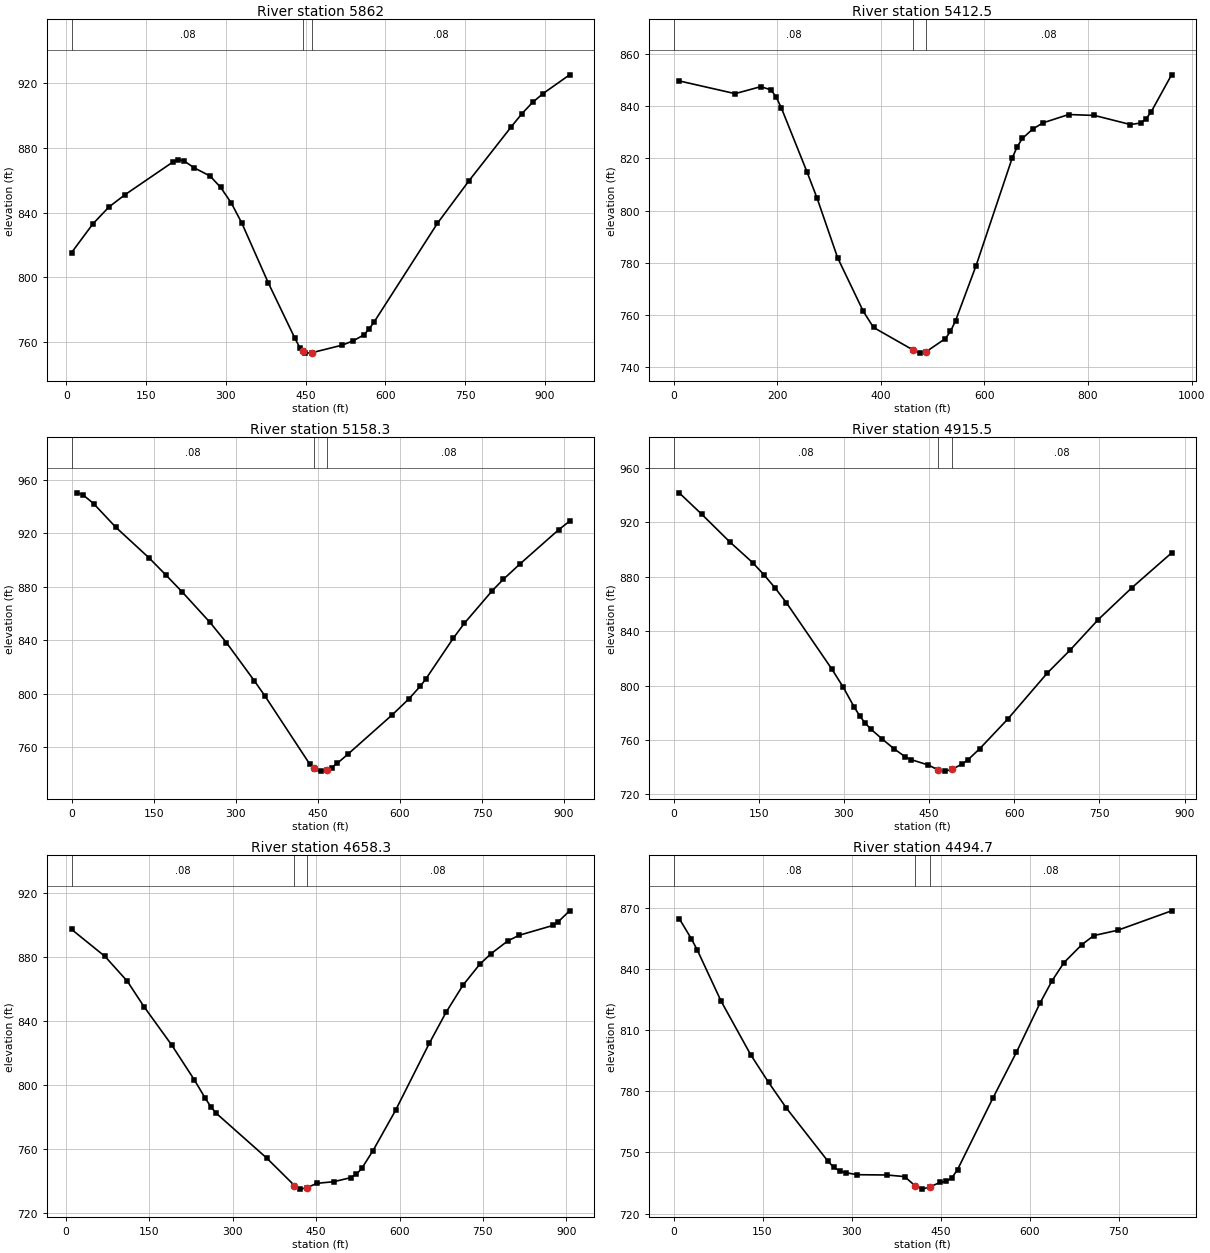
Type RM Length L Ch R = 1 ,5862    ,451.8,449.5,447.2
XS GIS Cut Line= 4
     1545501.104      388402.171     1545436.023       388654.48
     1545264.966      388911.065     1545069.154      389233.905
#Sta/Elev= 30
      10  815.18    50.1  832.97    80.2  843.39   110.2  850.96   200.4  871.24
   210.5  872.68   220.5  872.17   240.5   867.7   270.5  862.58   290.4  855.55
   310.3  845.93   330.2  833.43   379.9  796.47   429.7  762.31   439.6  756.09
  445.33  754.42   449.6  752.93   462.1  753.21   519.2   757.9   539.1  760.49
     559  764.07   568.9   767.6   578.9  772.18   698.1  833.37   757.7   859.8
   837.2  893.23   857.1  901.28     877  908.22   896.8  913.68   946.5  925.26
#Mann= 3 , 0 , 0
      10     .08       0  445.33    .045       0   462.1     .08       0
Bank Sta=445.33,462.1
XS Rating Curve= 0 ,0
Exp/Cntr=0.3,0.1

Type RM Length L Ch R = 1 ,5412.5  ,261.5,254.2,247.1
XS GIS Cut Line= 4
     1545087.535      388154.029     1545040.743      388467.242
     1544895.113      388726.139     1544876.155      389073.072
#Sta/Elev= 30
     9.9  849.72   118.8   844.8   168.2  847.47     188  846.26   197.9  843.55
   207.8  839.45   257.3  814.95   277.1  804.72   316.7  781.91   366.2   761.4
     386  755.22   462.6  746.56   475.1  745.39   487.6  745.94   524.6  750.95
   534.5  753.71   544.4  757.86     584  778.96   653.4  820.01   663.4   824.5
   673.3  827.65   693.2  831.22     713  833.61   762.6   836.8   812.3  836.45
   881.8  832.97   901.6  833.54   911.5  835.06   921.5   837.7   961.2  852.01
#Mann= 3 , 0 , 0
       0     .08       0   462.6    .045       0   487.6     .08       0
Bank Sta=462.6,487.6
XS Rating Curve= 0 ,0
Exp/Cntr=0.3,0.1

Type RM Length L Ch R = 1 ,5158.3  ,242,242.8,243.3
XS GIS Cut Line= 3
     1544845.162       388061.82     1544735.633      388503.434
     1544621.162      388943.835
#Sta/Elev= 30
    10.1  950.44    20.2  949.16    40.4  942.32    80.9  924.61   141.6  901.66
   171.9  889.05   202.2  876.13   252.8   853.4   283.1   838.1   333.7  809.71
   353.9  797.85   434.8  747.36   442.5  744.19   444.9   743.2     455  741.85
   467.5  742.98   475.2  744.56   485.3  747.63   505.6  754.78   586.4  784.22
   616.8  796.15     637  805.41   647.1  810.76   697.7  841.58   717.9  852.74
   768.5  876.98   788.7  885.49     819     897   889.8  922.66     910  929.19
#Mann= 3 , 0 , 0
       0     .08       0   442.5    .045       0   467.5     .08       0
Bank Sta=442.5,467.5
XS Rating Curve= 0 ,0
Exp/Cntr=0.3,0.1

Type RM Length L Ch R = 1 ,4915.5  ,265.6,257.2,250.9
XS GIS Cut Line= 4
     1544620.035      388011.861     1544532.195      388358.598
     1544479.029       388552.77     1544398.124       388860.21
#Sta/Elev= 30
     9.9  941.79    49.7     926    99.4  905.54   139.1  890.53     159   881.6
   178.8  871.83   198.7  860.94   278.2  812.47   298.1  799.29   317.9  784.31
   327.9  777.64   337.8  772.17   347.8  767.83   367.8  760.53   387.9  753.62
     408  747.58   418.1  745.55   448.3  741.62     466  737.94   478.5  737.07
     491  738.49   508.7  742.46   518.7  745.52   538.9  753.47   588.8  775.51
   658.4  809.36   698.1  826.03   747.8  848.55   807.4  872.13   876.9  897.57
#Mann= 3 , 0 , 0
       0     .08       0     466    .045       0     491     .08       0
Bank Sta=466,491
XS Rating Curve= 0 ,0
Exp/Cntr=0.3,0.1

Type RM Length L Ch R = 1 ,4658.3  ,168.7,163.6,157.7
XS GIS Cut Line= 3
      1544246.61       387961.03     1544263.409      388381.749
      1544246.61      388866.288
#Sta/Elev= 30
      10   897.3    70.2  880.38   110.3  864.88   140.4  848.95   190.5  824.83
   230.6  803.39   250.6  791.69   260.7  786.34   270.7  782.21   360.9   754.4
     411  737.18   421.1  734.93   433.6  735.86   451.4  738.56   481.7  739.57
     512  742.09   522.1  744.12   532.2  747.96   552.4  759.05   592.8  784.15
   653.4  825.99   683.7  845.45     714  862.35   744.3  875.47   764.5  882.07
   794.8   890.1     815  893.59   875.6  899.73   885.7  902.12   905.9   908.9
#Mann= 3 , 0 , 0
      10     .08       0     411    .045       0   433.6     .08       0
Bank Sta=411,433.6
XS Rating Curve= 0 ,0
Exp/Cntr=0.3,0.1

Type RM Length L Ch R = 1 ,4494.7  ,285.4,322.1,357.5
XS GIS Cut Line= 4
     1544205.253      388025.363     1544076.587      388296.481
      1544140.92      388576.789     1544099.563      388824.931
#Sta/Elev= 30
      10  864.61      30   854.9      40  849.39      80  824.34     130  797.96
   160.1  784.41   190.1   771.8   260.1  745.71   270.1  742.64   280.1  740.88
   290.1  740.03     310  739.05   359.6  738.91   389.4  738.12   406.6  733.74
   419.1  731.97   431.6  733.01   448.9  735.25   458.8  735.72   468.7  737.35
   478.6  741.56   538.1  776.61   577.8  799.14   617.9  823.49     638  834.34
   658.1  843.24   688.3  852.08   708.4  856.49   748.7   859.1   839.3  868.63
#Mann= 3 , 0 , 0
       0     .08       0   406.6    .045       0   431.6     .08       0
Bank Sta=406.6,431.6
XS Rating Curve= 0 ,0
Exp/Cntr=0.3,0.1

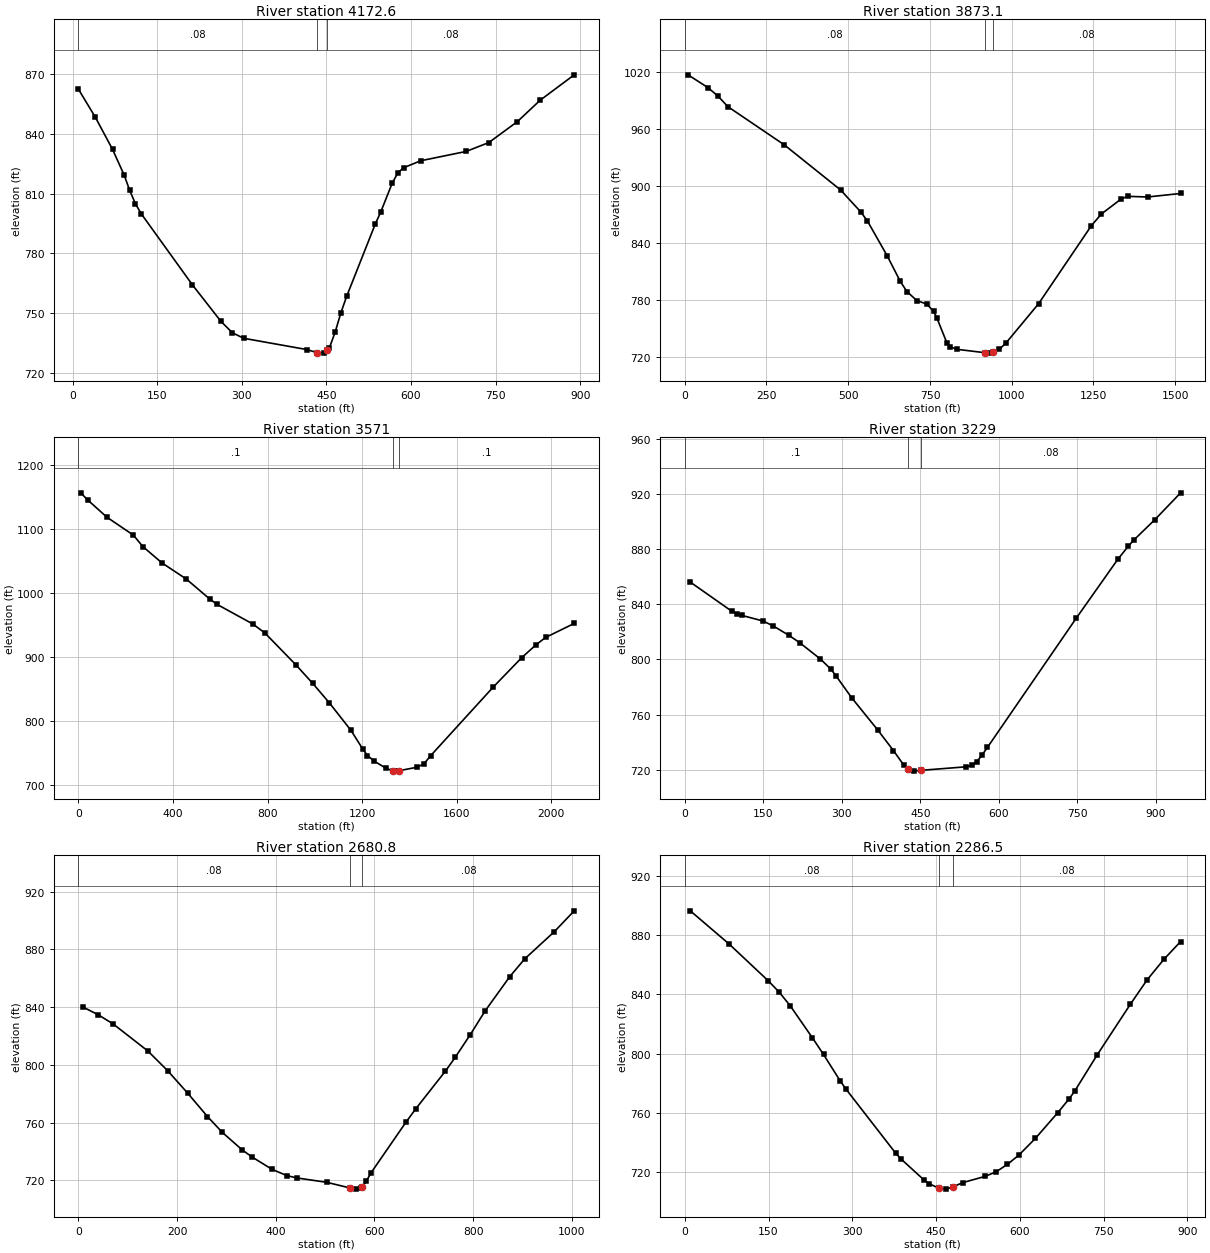
Type RM Length L Ch R = 1 ,4172.6  ,305.8,299.4,293.1
XS GIS Cut Line= 4
     1544163.896      387997.792     1544058.206      388227.553
     1543805.469      388356.219     1543558.323      388608.283
#Sta/Elev= 30
    10.1  862.61    40.5   848.3    70.8  832.26      91  819.59   101.2  811.66
   111.3  804.98   121.4  800.01   212.4  764.17     263  745.81   283.3  740.08
   303.5   737.3     415  731.66   432.8  730.16   445.3  729.85  451.24  731.65
   455.5  732.65   465.6  740.45   475.7  750.11   485.9  758.37   536.5  794.61
   546.6  800.94   566.8  815.34   576.9  820.55   586.9  823.04   617.2  826.55
   697.9  831.24   738.2  835.72   788.7  846.23     829  856.96   889.5  869.75
#Mann= 3 , 0 , 0
    10.1     .08       0   432.8    .045       0  451.24     .08       0
Bank Sta=432.8,451.24
XS Rating Curve= 0 ,0
Exp/Cntr=0.3,0.1

Type RM Length L Ch R = 1 ,3873.1  ,331.9,302.2,272.2
XS GIS Cut Line= 4
     1544641.799      387763.436     1543865.207       387961.03
     1543649.232      388140.244     1543515.971      388553.813
#Sta/Elev= 30
    10.1 1016.87      71 1003.38   101.4  994.59   131.9  983.38   304.3  943.19
   476.7  895.66   537.6  872.82   557.9  863.47   618.8  826.57   659.3  799.33
   679.6  788.68     710  779.19   740.5  775.54   760.8  767.89   770.9  761.11
   801.3  735.04   811.4  730.65   831.4  727.97   919.1  724.31   931.6  723.91
   944.1  724.64   961.7  727.85   981.8   734.3    1082  775.87  1243.7  858.14
    1274  870.32  1334.6  886.17  1354.8  888.96  1415.4  888.27  1516.5  891.98
#Mann= 3 , 0 , 0
       0     .08       0   919.1    .045       0   944.1     .08       0
Bank Sta=919.1,944.1
XS Rating Curve= 0 ,0
Exp/Cntr=0.3,0.1

Type RM Length L Ch R = 1 ,3571    ,347.2,342,337.1
XS GIS Cut Line= 4
     1543016.399      386700.753     1543504.641      387756.216
     1543554.901      388079.318     1543382.581        388660.9
#Sta/Elev= 30
    10.1 1157.05    40.4 1145.58   121.3 1118.75   232.6 1090.92     273 1072.89
   353.9 1047.31   455.1 1022.53   556.2  990.73   586.5  982.51   738.2  951.72
   788.8  937.76   920.2  887.74     991  858.89  1061.8  828.18  1152.8  785.34
  1202.6   756.1  1222.4  746.03  1252.1     737  1301.6  725.94  1328.8  722.11
  1341.3  721.63  1353.8  722.13  1430.5  727.62  1460.2  732.63  1489.9  745.96
  1752.8  852.62  1874.1  899.01  1934.7  919.19  1975.2  930.74  2096.5  952.69
#Mann= 3 , 0 , 0
       0      .1       0  1328.8    .045       0  1353.8      .1       0
Bank Sta=1328.8,1353.8
XS Rating Curve= 0 ,0
Exp/Cntr=0.3,0.1

Type RM Length L Ch R = 1 ,3229    ,531.8,548.1,564.2
XS GIS Cut Line= 3
     1543070.244       387638.91     1543211.613      388032.908
     1543378.638      388534.712
#Sta/Elev= 30
      10  856.15    89.7  834.92    99.7  833.05   109.6   831.8   149.5  827.82
   169.4  824.18   199.3  817.34   219.3  812.18   259.1   800.3   279.1  792.95
     289  788.09   318.9  772.23   368.8  748.83   398.7  733.96   418.6  723.35
     426  720.66   428.6  719.71   438.5  719.03     451   719.6   538.3  722.17
   548.3  723.12   558.3  725.97   568.3  730.76   578.3  736.19   747.9  829.74
   827.7  872.62   847.7  882.07   857.7  886.34   897.6  900.97   947.5  920.67
#Mann= 3 , 0 , 0
       0      .1       0     426    .045       0     451     .08       0
Bank Sta=426,451
XS Rating Curve= 0 ,0
Exp/Cntr=0.3,0.1

Type RM Length L Ch R = 1 ,2680.8  ,408.9,394.3,379.7
XS GIS Cut Line= 3
     1542918.736       387727.02     1542824.407      388108.111
     1542669.707      388700.499
#Sta/Elev= 30
    10.1  839.96    40.3  834.73    70.5  828.38   140.9  809.61   181.2  795.88
   221.5  780.41   261.7  764.15   291.9  753.13   332.2  740.99   352.3  736.06
   392.6  727.53   422.7   723.2   442.8  721.59     503  718.59   550.7  714.63
   563.2  713.84   573.3   714.4   575.7  715.56   583.3  719.25   593.3  725.26
   663.6  760.13   683.7  769.51   743.9  795.72     764  805.38   794.1   820.9
   824.2  837.39   874.4  861.26   904.5  873.49   964.7  892.42  1004.8  906.81
#Mann= 3 , 0 , 0
       0     .08       0   550.7    .045       0   575.7     .08       0
Bank Sta=550.7,575.7
XS Rating Curve= 0 ,0
Exp/Cntr=0.3,0.1

Type RM Length L Ch R = 1 ,2286.5  ,376.8,392.6,408.4
XS GIS Cut Line= 3
     1542318.801       387798.71     1542394.265      388138.296
     1542537.646      388658.995
#Sta/Elev= 30
     9.9  896.51    79.5  874.08   149.1  849.39     169  841.63   188.8  832.42
   228.6  810.73   248.5  799.48   278.3  781.68   288.2  776.34   377.9   732.7
   387.9  728.66   427.9   714.9   437.9  712.15   455.4  709.06   467.9  708.53
   480.4   710.1   497.9  712.94   537.9  717.14   557.9  720.31   577.9  725.32
   597.9  731.37   627.9  742.82   667.9  760.14   687.9  769.34   697.9  774.52
   737.9  798.85   797.9   833.4   827.9  849.88   857.9  863.73   887.9  875.77
#Mann= 3 , 0 , 0
       0     .08       0   455.4    .045       0   480.4     .08       0
Bank Sta=455.4,480.4
XS Rating Curve= 0 ,0
Exp/Cntr=0.3,0.1

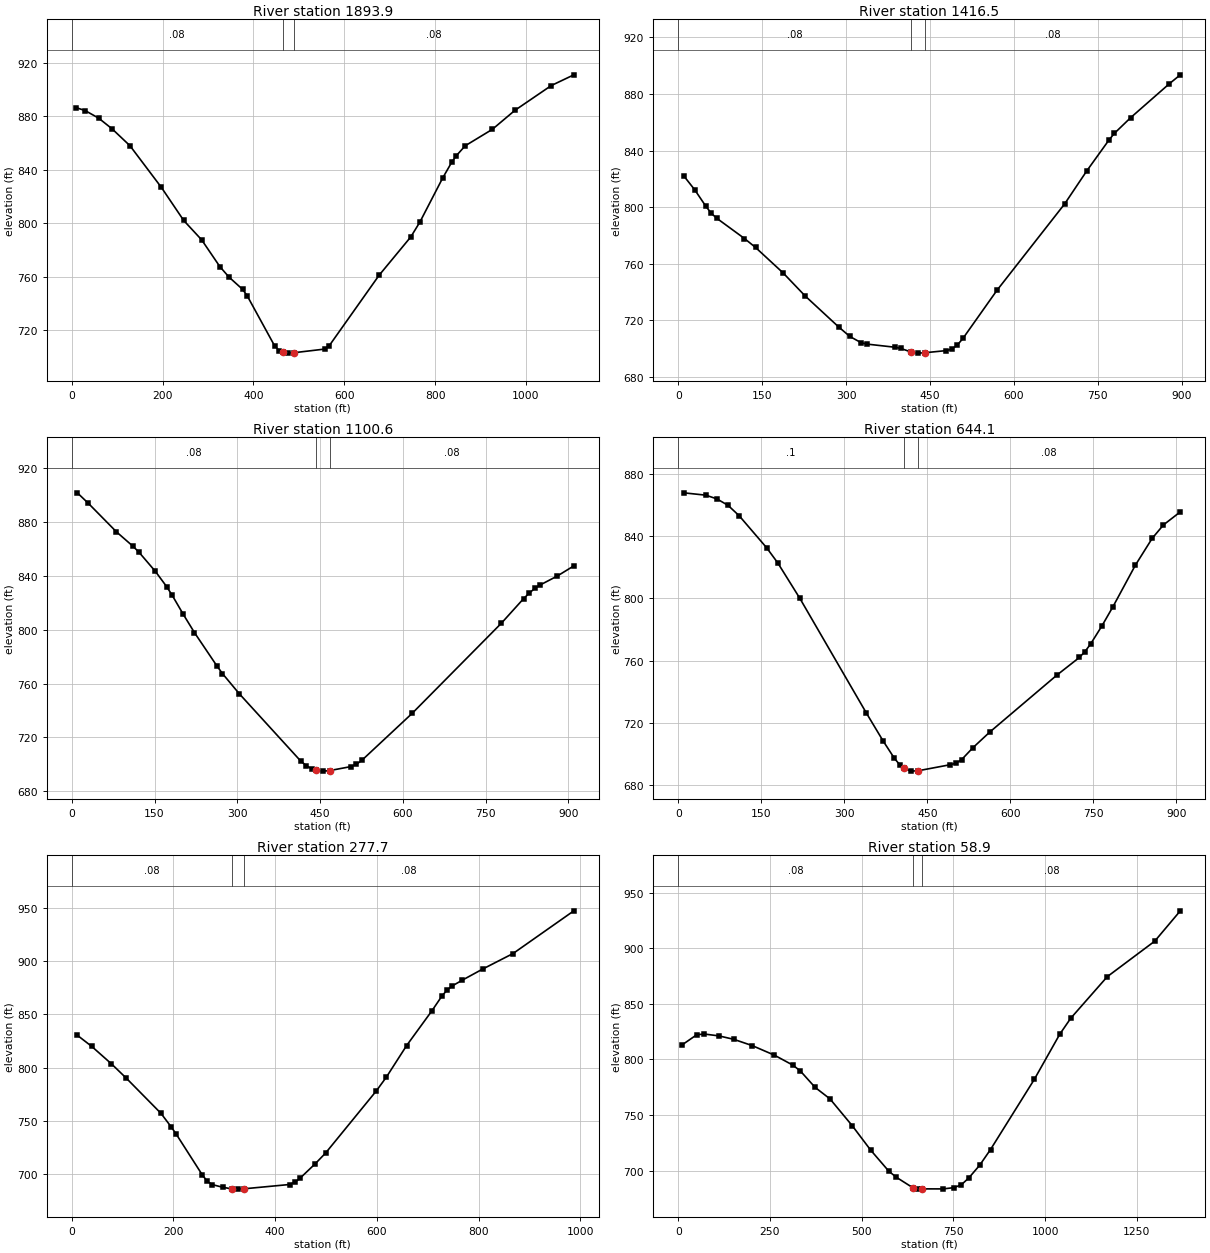
Type RM Length L Ch R = 1 ,1893.9  ,489.6,477.4,465.2
XS GIS Cut Line= 4
     1542216.926      387745.886      1542115.05      388002.462
     1542009.401       388368.46     1541869.793      388794.829
#Sta/Elev= 30
     9.9  886.32    29.6  884.14    59.2  878.51    88.7  870.55   128.2  857.89
   197.2  826.85   246.5   802.1   286.1  787.59   326.2  767.59   346.2  759.82
   376.3  750.61   386.3  745.84   446.5  708.57   456.5  704.94   464.1  703.73
   476.6  703.03   489.1  703.33   556.8  706.05   566.8  708.48   676.9  761.25
   746.7  789.89   766.7  800.98   816.5  833.65   836.5  845.47   846.4  850.31
   866.4  857.87   926.2  870.17     976  884.38  1055.8  902.83  1105.6  910.86
#Mann= 3 , 0 , 0
       0     .08       0   464.1    .045       0   489.1     .08       0
Bank Sta=464.1,489.1
XS Rating Curve= 0 ,0
Exp/Cntr=0.3,0.1

Type RM Length L Ch R = 1 ,1416.5  ,318.2,315.9,313.6
XS GIS Cut Line= 4
     1541533.981      387764.752     1541567.939      388028.874
     1541635.856      388447.697     1541669.815      388651.448
#Sta/Elev= 30
     9.9  822.12    29.6  812.21    49.3  800.67    59.2  795.63      69  792.12
   118.4  777.84   138.1  771.55   187.4  753.55   226.8  737.26   286.5  715.42
   306.7  708.63   326.9  704.21     337  703.26   387.5  701.01   397.6  700.19
   415.4  697.74   427.9  696.86   440.4  697.13   478.4  698.62   488.5  699.66
   498.6  702.51   508.7  707.22   569.4  741.17   690.6  802.36   729.9  825.56
   769.3  847.24   779.1  852.07   808.6  863.31   877.5   887.2   897.2  893.53
#Mann= 3 , 0 , 0
       0     .08       0   415.4    .045       0   440.4     .08       0
Bank Sta=415.4,440.4
XS Rating Curve= 0 ,0
Exp/Cntr=0.3,0.1

Type RM Length L Ch R = 1 ,1100.6  ,474.3,456.5,438.7
XS GIS Cut Line= 3
     1541175.963       387814.03     1541285.995      388255.525
     1541396.027       388697.02
#Sta/Elev= 30
    10.1  901.68    30.3  893.78    80.9  872.73   111.2  861.89   121.3  857.81
   151.7  843.25   171.9  832.04     182  825.58   202.2  811.36   222.4  797.84
   262.9   773.2     273  767.48   303.3   752.6   414.6  702.62   424.7  699.14
   434.8  696.74   442.5  695.73     455  694.97   467.5  695.38   505.6  698.31
   515.7  699.99   525.8  703.01   616.8  737.82   778.6  804.81     819  823.12
   829.1  827.17   839.2  830.71   849.3  833.32   879.7  839.81     910  847.42
#Mann= 3 , 0 , 0
       0     .08       0   442.5    .045       0   467.5     .08       0
Bank Sta=442.5,467.5
XS Rating Curve= 0 ,0
Exp/Cntr=0.3,0.1

Type RM Length L Ch R = 1 ,644.1   ,349.4,366.4,383.1
XS GIS Cut Line= 3
     1540756.706      388025.101     1540798.211      388342.048
     1541254.766      388711.819
#Sta/Elev= 30
      10  867.85    49.9  866.34    69.9  863.95    89.9  859.83   109.9  853.21
   159.8  832.55   179.8  822.88   219.8  800.06   339.9  726.47   370.3  708.47
   390.6  697.37   400.7  693.03   408.4     691   420.9  689.15   433.4  689.38
   491.9   693.3     502  694.25   512.1  696.56   532.4  704.16   562.8   714.2
   684.3  750.84   724.8  762.13     735  765.95   745.1  770.79   765.4   782.3
   785.6   794.8   826.1  821.45   856.5  838.68   876.8  847.27   907.2  855.63
#Mann= 3 , 0 , 0
       0      .1       0   408.4    .045       0   433.4     .08       0
Bank Sta=408.4,433.4
XS Rating Curve= 0 ,0
Exp/Cntr=0.3,0.1

Type RM Length L Ch R = 1 ,277.7   ,218.5,218.9,219.2
XS GIS Cut Line= 4
     1540696.336      388240.172     1540639.738      388406.192
     1540673.696      388738.231     1540941.592      389134.415
#Sta/Elev= 30
     9.7  830.82      39  820.04      78  803.62   107.2  790.21   175.4  757.27
   195.6  744.52   205.7  737.58   256.3  699.91   266.4  693.61   276.5  690.49
   296.8  688.04   314.6  686.54   327.1  686.29   339.6  686.64   428.3  690.62
   438.4  692.67   448.5  696.31   478.8  710.05   499.1  720.05   598.8  778.19
   618.8  791.25   658.6  820.79   708.4  853.38   728.4  867.43   738.3  872.77
   748.3  876.61   768.2  882.03   808.1  892.38   867.9  906.94   987.4  946.91
#Mann= 3 , 0 , 0
       0     .08       0   314.6    .045       0   339.6     .08       0
Bank Sta=314.6,339.6
XS Rating Curve= 0 ,0
Exp/Cntr=0.3,0.1

Type RM Length L Ch R = 1 ,58.9    ,48.5,58.9,69.3
XS GIS Cut Line= 4
     1540575.594      387991.142     1540435.986      388496.748
     1540537.862      388858.973     1540907.633      389145.734
#Sta/Elev= 30
    10.1  813.03    50.4  822.23    70.6  822.91     111  821.22   151.3  818.14
   201.7  812.49   262.3  803.87   312.7  794.89   332.9  789.67   373.2  774.91
   413.6  764.61   474.1  740.58   524.5  718.57     574  699.61   593.8   694.3
   640.8  684.45   653.3  683.46   665.8  683.69   722.6  683.66   752.3  684.84
   772.1  687.49   791.9  693.45   821.6  704.87   851.3  719.05   970.5  782.03
  1040.2  822.79  1070.1  837.12  1169.6  874.46    1299  906.38  1368.7  933.65
#Mann= 3 , 0 , 0
       0     .08       0   640.8    .045       0   665.8     .08       0
Bank Sta=640.8,665.8
XS Rating Curve= 0 ,0
Exp/Cntr=0.3,0.1

Chan Stop Cuts=-1
Use User Specified Reach Order=0